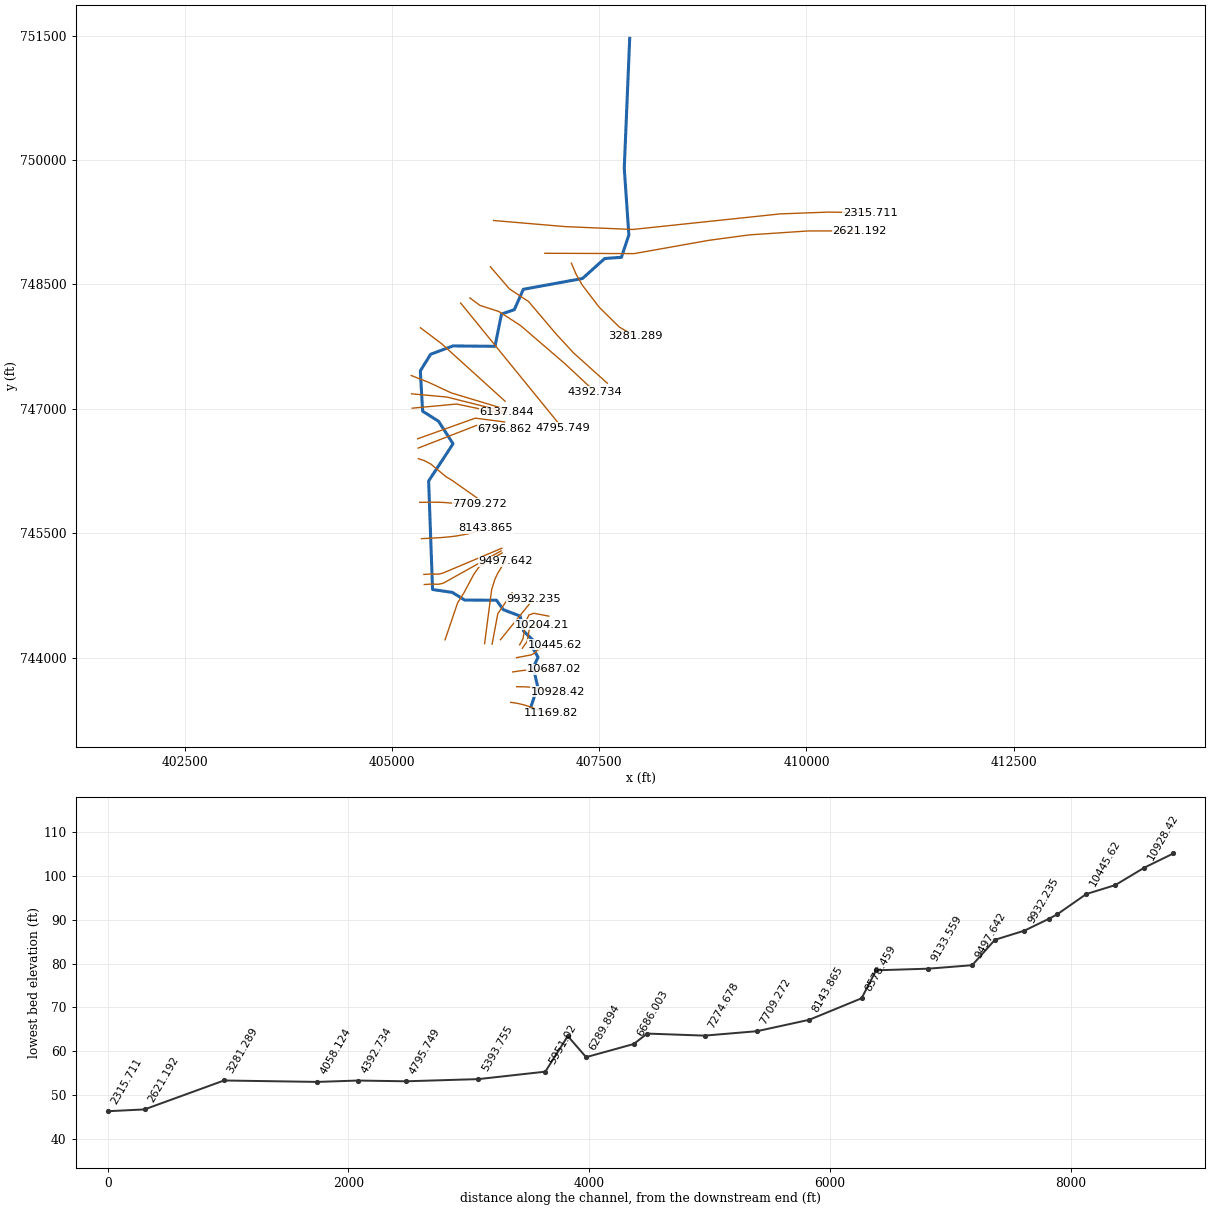
--- 2838_ras.prj (project) ---

Proj Title=2838
Current Plan=p01
Default Exp/Contr=0.3,0.1
English Units
Geom File=g01
Flow File=f01
Plan File=p01
Y Axis Title=Elevation
X Axis Title(PF)=Main Channel Distance
X Axis Title(XS)=Station
BEGIN DESCRIPTION:
RFD model 2838 exported to HEC-RAS
END DESCRIPTION:

--- 2838_ras.p01 (plan) ---

Plan Title=Plan 01
Program Version=4.10
Short Identifier=Plan 01
Geom File=g01
Flow File=f01
Subcritical Flow
Calc Critical at every XS
Secant Critical Depth

--- 2838_ras.f01 (steady flow) ---

Flow Title=Flow 01
Program Version=5.01
Number of Profiles= 6
Profile Names=10yr,25yr,50yr,100yr,100plus,500yr
River Rch & RM=2838,29,11169.82
  110.71  199.03  289.81  384.49  561.36 1168.62
River Rch & RM=2838,29,9686.491
  163.44  294.09  428.64  568.82  830.48 1636.03
River Rch & RM=2838,29,9133.559
  164.84  296.63  432.37  573.81  837.76 1648.51
River Rch & RM=2838,29,8699.789
  166.69     300  437.33  580.43  847.43 1665.09
River Rch & RM=2838,29,8578.459
  168.53  303.36  442.27  587.03  857.07  1681.6
River Rch & RM=2838,29,8143.865
  210.65  379.99  554.87  737.29 1076.45 2049.66
River Rch & RM=2838,29,7709.272
  220.03  397.11  580.07  770.99 1125.65    2131
River Rch & RM=2838,29,7274.678
  239.24  432.24  631.89  840.36 1226.92 2297.45
River Rch & RM=2838,29,6796.862
  321.88  583.51  855.14  1139.3 1663.37 2994.57
River Rch & RM=2838,29,6289.894
  324.44   588.2  862.08  1148.6 1676.96  3015.9
River Rch & RM=2838,29,6137.844
  329.53  597.57  875.92 1167.17 1704.06 3058.37
River Rch & RM=2838,29, 5951.02
  330.51  599.36  878.58 1170.73 1709.26 3066.51
River Rch & RM=2838,29,5393.755
  369.75   671.5  985.37 1314.07 1918.54 3391.84
River Rch & RM=2838,29,4795.749
  376.07  683.09  1002.5 1337.03 1952.07 3443.31
River Rch & RM=2838,29,4392.734
  382.08  694.07 1018.69 1358.68 1983.68 3491.38
River Rch & RM=2838,29,4058.124
  386.54  702.21 1030.68 1374.71 2007.08 3526.87
River Rch & RM=2838,29,3281.289
  409.22  743.64 1091.75 1456.36 2126.29 3706.85
River Rch & RM=2838,29,2621.192
  463.66  843.57 1239.56 1654.54 2415.63 4141.17
River Rch & RM=2838,29,1894.466
  463.28  842.88 1238.54 1653.19 2413.66 4138.28
Boundary for River Rch & Prof#=2838,29,1
Up Type= 0
Dn Type= 2
Boundary for River Rch & Prof#=2838,29,2
Up Type= 0
Dn Type= 2
Boundary for River Rch & Prof#=2838,29,2
Up Type= 0
Dn Type= 2
Boundary for River Rch & Prof#=2838,29,2
Up Type= 0
Dn Type= 2
Boundary for River Rch & Prof#=2838,29,2
Up Type= 0
Dn Type= 2
Boundary for River Rch & Prof#=2838,29,2
Up Type= 0
Dn Type= 2

--- 2838_ras.g01 (geometry) ---

Geom Title=2838
Program Version=4.10

River Reach=2838,29
Reach XY= 30
406674.948322803743404.239314854406757.726100683743655.350425974
406705.503878266743884.794870362406762.448322803744007.572648212
406694.114989281744129.239314839406704.184433728744211.635148197
406588.906656057744322.051814809406546.545544833744503.996259257
406343.767767072744581.079592645406261.128878206744694.968481526
405877.795544922744696.774037033405728.628878176744789.274037063
405490.134271968744823.833185772405442.795544833746131.287926003
405737.378878176 746580.31570375405562.063325793746851.872019947
405370.396848142746972.705601156405342.619091898747458.816634864
405466.924330831747658.816762358405736.368858278747759.511054739
406242.766348004747754.666725025406321.927489281748143.683759376
406476.371933877748196.461537033406585.260822713748442.017092645
407298.594155997748572.017092571407566.510822624748812.989314809
407768.052535683748827.336427167407857.896526456749096.455398664
407802.341068923749901.316574827407867.956145704751466.306223929

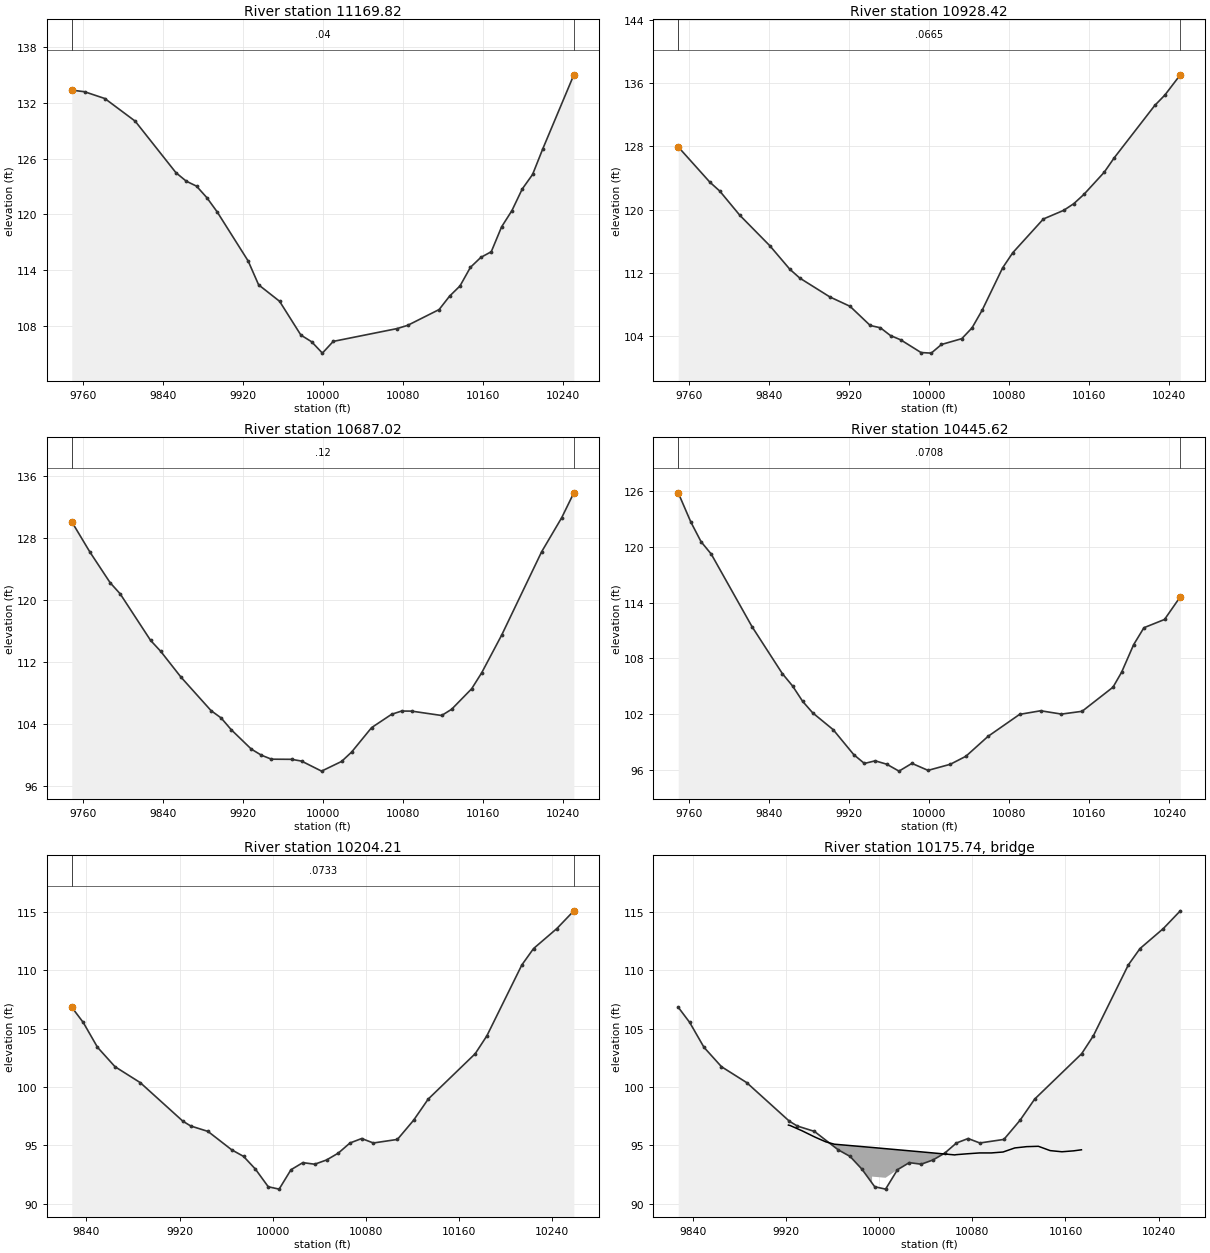
Type RM Length L Ch R = 1 ,11169.82,241.402700,241.402700,241.402700
XS GIS Cut Line= 6
406432.352961824743464.614796097406512.141771489743452.583490326
406592.363423459743433.786371506406643.312949461743417.898388771
406766.047396376743372.165093037406914.973022376743331.391193968
#Sta/Elev= 30
9749.061133.33779761.851133.16259782.077132.43779812.417130.01299853.229124.4798
  9863.5123.57519873.771123.04059884.042121.81439894.313120.29749925.383 115.018
9935.858112.45749956.808110.69369978.088107.07299988.845 106.3539999.612105.1347
10010.43106.392310074.32107.767710084.88108.115310116.31 109.80910126.73111.2427
10137.16112.337710147.58114.333910158.01   115.410168.43116.008310178.76118.6769
10189.08120.4205 10199.4122.738510209.72124.291310220.04127.070110250.98134.9768
#Mann= 3 , 0 , 0
9749.061    0.04       09749.061    0.04       010250.98    0.04       0
#XS Ineff= 2 , 0
       0                               0
Bank Sta=9749.061,10250.98
Exp/Cntr=0.3,0.1

Type RM Length L Ch R = 1 ,10928.42,241.402700,241.402700,241.402700
XS GIS Cut Line= 6
406503.459058083743652.896107249406613.524437079743651.134587124
406681.395439973743645.615718445406724.941970131743638.601682657
406870.730280191743609.770096851407000.268389477743589.903381282
#Sta/Elev= 30
9749.038127.92039780.583123.48269790.584122.34419810.587119.29589840.591115.4497
9860.598112.48229870.631111.3588 9900.73 108.9799920.796107.80319940.992105.3809
9951.121105.0955 9961.25 104.1099971.379103.57619991.778101.967710001.98101.8933
10012.17102.982310032.56103.721510042.75105.079910052.94107.323210073.32112.6511
10083.52114.571610114.09118.824410134.37119.913710144.49120.7571 10154.6121.9265
10174.84124.712410184.95126.551510225.42133.150210235.54134.465610250.99137.0198
#Mann= 3 , 0 , 0
9749.038  0.0665       09749.038  0.0665       010250.99  0.0665       0
#XS Ineff= 2 , 0
       0                               0
Bank Sta=9749.038,10250.99
Exp/Cntr=0.3,0.1

Type RM Length L Ch R = 1 ,10687.02,241.402600,241.402600,241.402600
XS GIS Cut Line= 6
406457.090238887743830.710610953406567.092722945743847.071849722
406674.888294666743858.380386417406705.231172742743859.809866978
406793.511308555743862.892916361406957.170902215743863.853636744
#Sta/Elev= 30
9749.024130.07499767.131126.17539787.351122.21949797.461 120.7729827.791114.7809
9837.901113.36979858.121 110.0499888.297105.71379898.352104.77139908.407103.2627
9928.516100.75399938.57199.969369948.62699.453149968.73599.435149978.74699.20763
9998.76997.9120710018.7899.1611510028.79 100.368 10048.8 103.52410068.81105.2419
10078.82105.662410088.82105.651510118.82105.086810128.82105.892210148.82108.5322
10158.82 110.58710178.82115.452410218.82126.210710238.83130.5912   10251 133.806
#Mann= 3 , 0 , 0
9749.024    0.12       09749.024    0.12       0   10251    0.12       0
#XS Ineff= 2 , 0
       0                               0
Bank Sta=9749.024,10251
Exp/Cntr=0.3,0.1

Type RM Length L Ch R = 1 ,10445.62,241.402700,241.402700,241.402700
XS GIS Cut Line= 6
406502.665298693744002.466076475406677.662002104744035.597977773
406709.145566477744050.495463801406752.005372574744090.607139995
406783.819964648744108.301099685406970.310701343744159.037199518
#Sta/Elev= 30
 9749.09125.80889761.679122.66759771.884120.5526 9782.09119.21579822.782111.4187
9853.176106.35119863.308105.03499873.439103.37159883.571102.1232 9903.97100.3237
9924.53197.636749935.13896.690069945.91896.971259957.42396.611849969.71695.86384
9982.65596.698549998.75895.9451410021.0296.6018710036.5897.4614910058.7499.60658
10090.27101.970810111.29 102.35910132.11102.000910152.71102.300510183.61104.8959
10192.23106.510710204.21109.466610214.51111.293810235.11112.182310250.88114.6259
#Mann= 3 , 0 , 0
 9749.09  0.0708       0 9749.09  0.0708       010250.88  0.0708       0
#XS Ineff= 2 , 0
       0                               0
Bank Sta=9749.09,10250.88
Exp/Cntr=0.3,0.1

Type RM Length L Ch R = 1 ,10204.21,68.491200,68.491200,68.491200
XS GIS Cut Line= 6
406573.614135024744116.938533874406632.466532972744200.487190576
406661.967722979744374.534019994406672.818417427744384.299644994
406695.604875859744389.724992217406809.537167427744397.320478322
#Sta/Elev= 30
9827.465 106.8459837.325105.53759849.557103.40859864.601101.74099886.253100.3764
9922.94997.058949929.66196.651619944.43896.186979964.80294.608499974.98594.04326
9985.16792.951749996.20191.4365710005.5391.2337510015.7192.89849 10025.993.50695
10036.0893.3724110046.2693.7356410056.3794.3272810066.3995.1946510076.4195.57609
10086.45 95.194610107.1195.4995410121.0197.1461310133.5498.96015 10173.9102.8554
10183.92104.388810213.99110.479310224.01111.881310244.05113.599610258.62115.1197
#Mann= 3 , 0 , 0
9827.465  0.0733       09827.465  0.0733       010258.62  0.0733       0
#XS Ineff= 2 , 0
       09963.499        10074.66       0
Bank Sta=9827.465,10258.62
Exp/Cntr=0.3,0.1

Type RM Length L Ch R = 3 ,10175.74,,,
BEGIN DESCRIPTION:
END DESCRIPTION:
Bridge Culvert--1,0,-1,-1, 0
Deck Dist Width WeirC Skew NumUp NumDn MinLoCord MaxHiCord MaxSubmerge Is_Ogee
26.230600,16.030000,2.6,0, 25, 25, , , 0.95, 0, 0,0,,
 9922.10 9923.62 9933.82 9944.02 9945.53 9954.23 9961.53 9993.91 9993.9110036.35
10036.3510064.9610065.9610076.0710086.1910096.3010106.4110116.5210125.8010126.63
10136.7410146.8510156.9610167.0810173.71
   96.73   96.69   96.24   95.74   95.67   95.29   95.09   94.81   94.81   94.43
   94.43   94.17   94.19   94.27   94.34   94.34   94.42   94.77   94.87   94.88
   94.91   94.54   94.44   94.52   94.61
 -903.27 -903.31 -903.76 -904.26 -904.33 -904.71 -904.91 -905.19   92.31   91.93
 -905.57 -905.83 -905.81 -905.73 -905.66 -905.66 -905.58 -905.23 -905.13 -905.12
 -905.09 -905.46 -905.56 -905.48 -905.39
 9922.10 9923.62 9933.82 9944.02 9945.53 9954.23 9961.53 9991.61 9991.6110034.05
10034.0510064.9610065.9610076.0710086.1910096.3010106.4110116.5210125.8010126.63
10136.7410146.8510156.9610167.0810173.71
   96.73   96.69   96.24   95.74   95.67   95.29   95.09   94.83   94.83   94.45
   94.45   94.17   94.19   94.27   94.34   94.34   94.42   94.77   94.87   94.88
   94.91   94.54   94.44   94.52   94.61
 -903.27 -903.31 -903.76 -904.26 -904.33 -904.71 -904.91 -905.17   92.33   91.95
 -905.55 -905.83 -905.81 -905.73 -905.66 -905.66 -905.58 -905.23 -905.13 -905.12
 -905.09 -905.46 -905.56 -905.48 -905.39
BR Coef=-1 , 0 , 0 ,, 0 ,,,0.8,0,1,0,
WSPro=,,,, 1 ,,,, 0 ,,,, 0 ,,,,-1 ,-1 ,-1 , 0 , 0 , 0 , 0 , 0
BC Design=,, 0 ,, 0 ,,,,,,

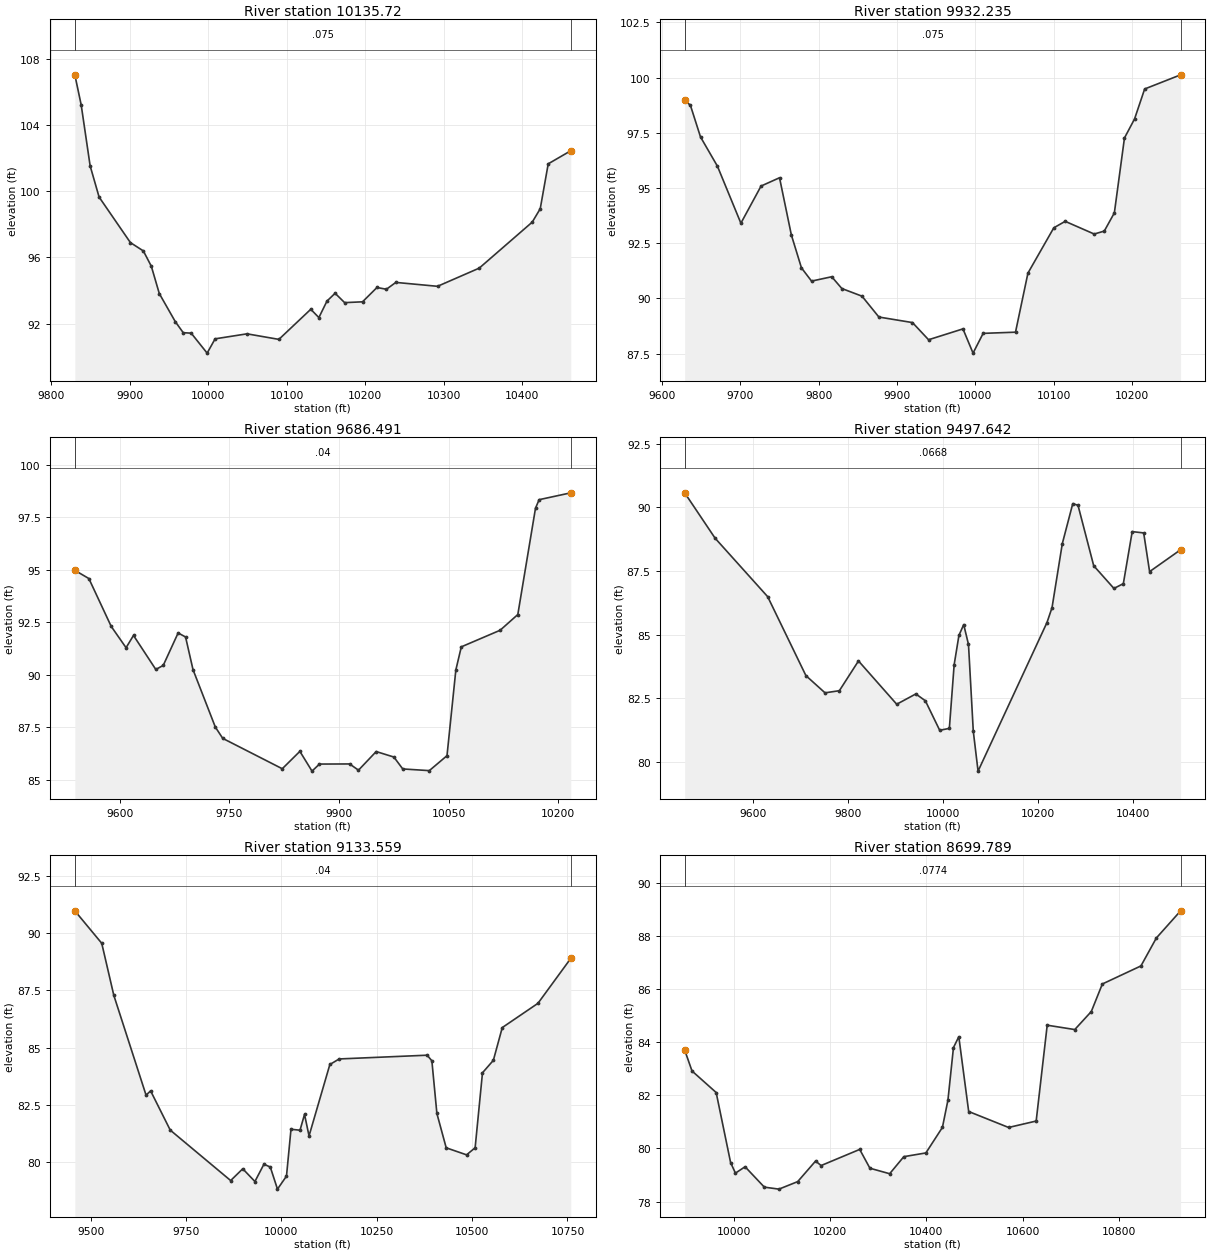
Type RM Length L Ch R = 1 ,10135.72,203.487300,203.487300,203.487300
XS GIS Cut Line= 6
406540.975246131744157.910756096406580.558579564744230.132978305
406618.891778409744446.037454844406652.332306325744517.155547768
406712.011125773744537.771867216406893.217722982744503.049644977
#Sta/Elev= 30
9830.024107.02599838.108105.21299849.512101.53149860.91599.648319900.81796.89802
9917.32596.394449927.48295.469669937.63893.820269957.95192.129669968.10791.45877
9978.264 91.43069998.57790.2250310008.7391.0879810049.3691.3900810089.9891.05473
10130.6192.8723510140.9392.3717210151.2693.36805 10161.693.8389510173.7793.27321
10196.5593.3229310214.9594.1871410226.9794.0809710238.99 94.494210292.0994.25892
10345.2295.3560910412.7798.1343110422.9598.9420410433.13101.653210461.86102.4425
#Mann= 3 , 0 , 0
9830.024   0.075       09830.024   0.075       010461.86   0.075       0
#XS Ineff= 2 , 0
       09957.037        10097.98       0
Bank Sta=9830.024,10461.86
Exp/Cntr=0.3,0.1

Type RM Length L Ch R = 1 ,9932.235,245.744500,245.744500,245.744500
XS GIS Cut Line= 2
406308.634389639744219.317006111406707.939945221744710.636450529
#Sta/Elev= 30
9628.82598.977369636.14898.743499649.03497.311099670.62995.987269700.57893.40447
9726.35195.087719749.90695.463189765.00992.872889777.89591.381859790.78190.78187
9816.553 90.97939829.43990.446129855.21290.09911 9876.75 89.15479919.64288.90341
9940.17288.125919984.07388.617939996.95987.5198310009.8488.4151210051.1688.46847
10067.0291.1437510100.0593.1961110114.5893.4890610151.5992.9148110164.4893.04733
10177.3693.8730210190.2597.2649510203.1498.1269410216.0299.4837210261.94 100.125
#Mann= 3 , 0 , 0
9628.825   0.075       09628.825   0.075       010261.94   0.075       0
#XS Ineff= 2 , 0
       09910.197        10048.15       0
Bank Sta=9628.825,10261.94
Exp/Cntr=0.3,0.1

Type RM Length L Ch R = 1 ,9686.491,188.849100,188.849100,188.849100
XS GIS Cut Line= 3
406208.298380792744166.137996078406276.874769628744532.023412749
406449.400811315744784.844593316
#Sta/Elev= 30
9538.67894.976359557.86894.58606 9588.3992.311359608.73991.295339618.91391.87933
9649.43590.260239659.60990.454929679.95791.997429690.13291.805599700.30690.25312
9730.82887.520659741.002 86.98189822.39585.537389846.47486.364359863.09285.42389
9873.266   85.769914.53885.765349926.64485.469339950.85786.35487 9975.0786.09391
9987.17785.52789 10023.585.4474810047.7186.1584310059.8290.2380110067.2891.33654
10120.3592.1255610144.5692.8727610168.7797.9333610173.7298.3382810217.0198.66393
#Mann= 3 , 0 , 0
9538.678    0.04       09538.678    0.04       010217.01    0.04       0
#XS Ineff= 2 , 0
       0 9950.91        10097.17       0
Bank Sta=9538.678,10217.01
Exp/Cntr=0.3,0.1

Type RM Length L Ch R = 1 ,9497.642,364.082800,364.082800,364.082800
XS GIS Cut Line= 6
 406117.58657524744171.346329406406203.004311621744823.664655402
406241.404214621744945.806255057406275.116303384745017.809858188
406330.463762999745107.974428102406375.928834766745166.743304342
#Sta/Elev= 30
9455.06690.569389519.22188.785759630.08786.486949710.71783.383599751.03182.70688
9781.26782.790899821.58283.960839902.21282.25859 9942.4982.663499962.61382.39484
9992.83881.23449 10013.281.30987 10023.383.8081610033.3984.9655210043.4885.38958
10053.5684.6072210063.6581.2012110073.7479.6291710219.0885.4711210229.73 86.0566
10251.38 88.570410273.4790.1461110284.5190.0780410317.6387.7022110360.2386.81071
 10380.186.99923 10398.889.04489   1042388.9929210435.4687.4715910500.8888.33248
#Mann= 3 , 0 , 0
9455.066  0.0668       09455.066  0.0668       010500.88  0.0668       0
#XS Ineff= 2 , 0
       09898.091        10048.39       0
Bank Sta=9455.066,10500.88
Exp/Cntr=0.3,0.1

Type RM Length L Ch R = 1 ,9133.559,433.769700,433.769700,433.769700
XS GIS Cut Line= 6
 405641.02407521744218.221329406405792.443299621744663.397660956
405870.155846775 744786.57767643405987.889718056745008.038018391
 406051.31777662745096.859288394 406328.52407521745265.096329406
#Sta/Elev= 30
9458.44790.965839528.98289.55127 9560.67 87.28029645.171 82.9338 9657.1283.11886
9708.54781.410389866.98679.211039898.67479.724569930.56579.169799954.22379.92411
9970.89979.799519989.70978.8377310013.33 79.404710025.1581.44592 10048.881.40536
10060.6382.0953410072.4581.1564210127.0484.2691910151.5584.5110110382.0984.67415
10394.4884.4305710407.6582.1337810432.0580.6382210485.4980.3318610507.9180.64079
10527.1883.9077110555.6884.4507310579.0785.8780610672.6586.9357610758.6688.89235
#Mann= 3 , 0 , 0
9458.447    0.04       09458.447    0.04       010758.66    0.04       0
#XS Ineff= 2 , 0
       09853.169        10070.61       0
Bank Sta=9458.447,10758.66
Exp/Cntr=0.3,0.1

Type RM Length L Ch R = 1 ,8699.789,121.330000,121.330000,121.330000
XS GIS Cut Line= 6
405389.818541646744884.291862503405470.094639599744889.111110687
405556.478768229744887.422598168405592.240788966744893.006515041
405622.577377349744901.905307442406316.937659323745289.572399765
#Sta/Elev= 30
9898.16283.701149913.41282.913749963.54182.103549993.562 79.465810003.5779.06821
 10023.679.3087610063.6378.5407910093.9778.4664810132.9278.7497110170.0579.52379
 10181.579.3538210261.6779.9614210282.8679.2532810323.89 79.0461 10353.379.68875
10399.1179.8288810433.4780.7905810444.9281.8168710456.3883.7942410467.4984.20433
   1048881.3883910570.91 80.787310628.1781.0294810651.0884.6376110708.3484.47328
 10742.785.1524910765.6186.1887710845.78 86.868810877.7687.9200110928.1788.94297
#Mann= 3 , 0 , 0
9898.162  0.0774       09898.162  0.0774       010928.17  0.0774       0
#XS Ineff= 2 , 0
       09930.483        10119.84       0
Bank Sta=9898.162,10928.17
Exp/Cntr=0.3,0.1

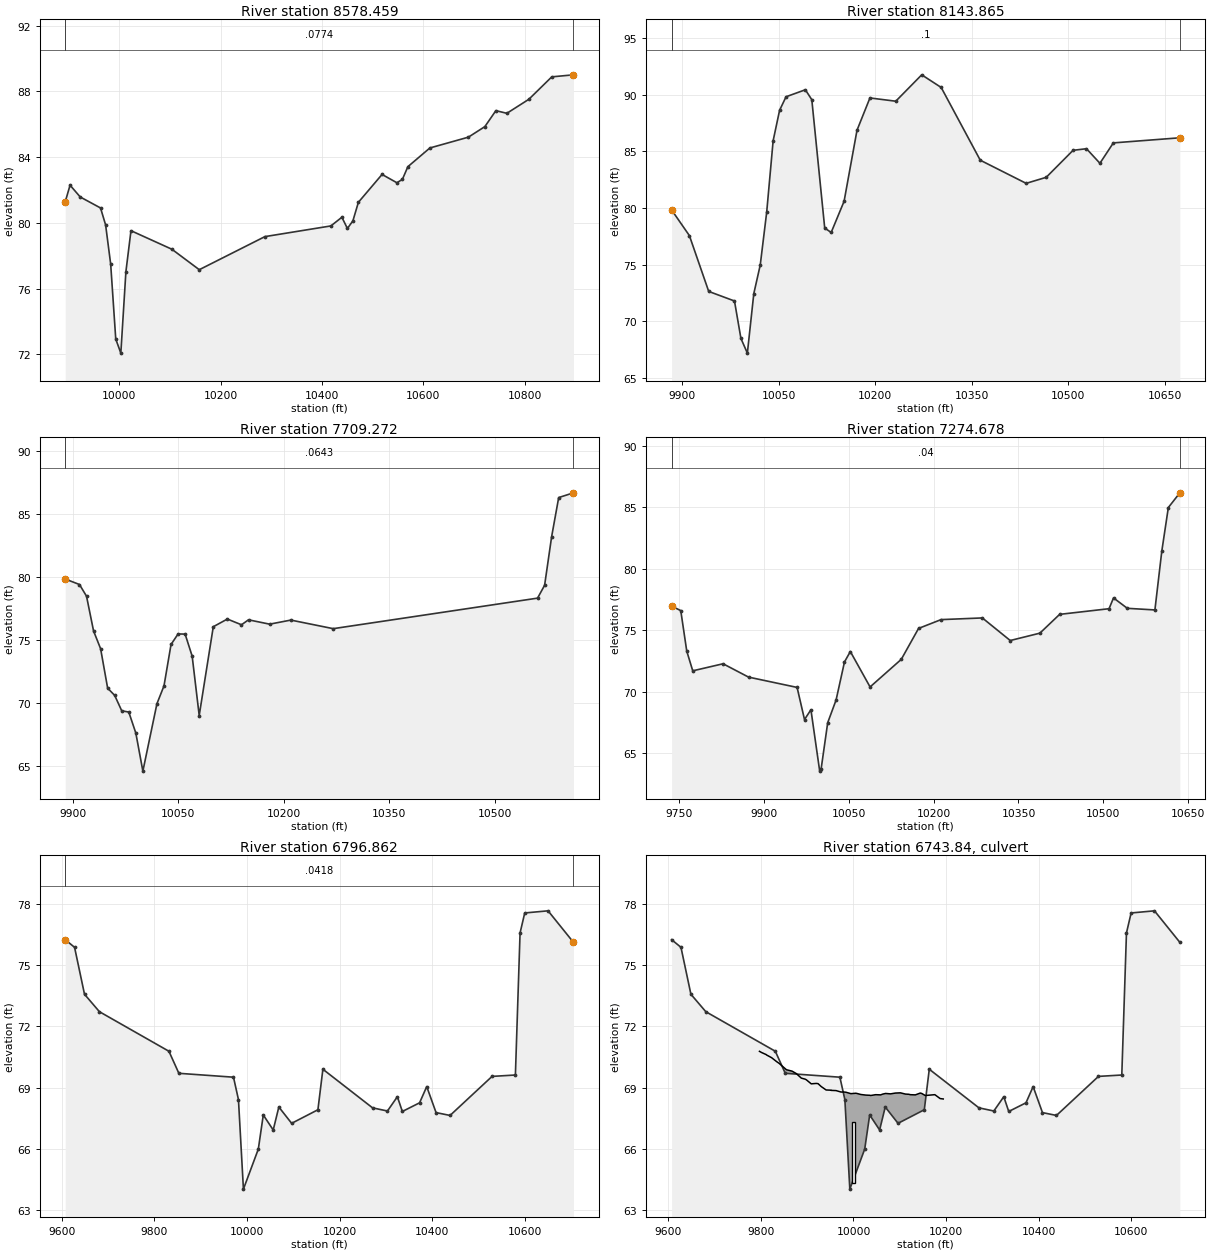
Type RM Length L Ch R = 1 ,8578.459,434.593600,434.593600,434.593600
XS GIS Cut Line= 6
405385.478263855745005.819640279405465.754361808745010.638888463
405552.138490438745008.950375929405587.900511175745014.534292817
405618.237099528745023.433085218406326.109062791745321.621758685
#Sta/Elev= 30
9893.37481.276589902.93982.295519923.02981.577949963.094 80.90969973.09679.87908
9983.10777.494069993.11872.9362710003.1372.0783610013.1477.0337610023.1579.52732
10103.9178.3981710157.9277.1537710287.3879.1665410417.59 79.8172 10439.380.34549
10450.1579.66297   1046180.1229110471.85 81.253910518.5682.9498310547.8182.44474
10558.6682.6481210569.5183.4217610612.9184.5597110688.8785.2170710721.4285.85975
10743.1386.8301810764.8386.6690110808.2387.5224310853.4388.8860710896.2489.00988
#Mann= 3 , 0 , 0
9893.374  0.0774       09893.374  0.0774       010896.24  0.0774       0
#XS Ineff= 2 , 0
       0                10054.08       0
Bank Sta=9893.374,10896.24
Exp/Cntr=0.3,0.1

Type RM Length L Ch R = 1 ,8143.865,434.593600,434.593600,434.593600
XS GIS Cut Line= 6
405357.429289162745436.813949749405579.667796582745448.836600378
405699.417924315745459.232359558 405773.41662246745468.518624008
405910.398400962745493.042586759406134.102778912745559.582729876
#Sta/Elev= 30
9883.54679.824679911.17677.557389941.21572.626529981.26671.780749991.27968.47408
10001.2967.1766310011.3172.4367110021.3274.9622310031.3479.6336310041.3585.93611
10051.3688.6218510061.3889.8172410091.4290.4375810101.4489.55942 10121.5 78.2263
10131.5477.8321310151.6280.5891610171.6986.8622210191.7789.7134910231.9489.42552
10272.25 91.7559 10302.590.6413210363.2584.2149610434.5782.1713510465.7482.70414
10507.4785.0882810528.3485.23036 10549.283.9441110570.0785.7444410673.4686.19534
#Mann= 3 , 0 , 0
9883.546     0.1       09883.546     0.1       010673.46     0.1       0
#XS Ineff= 2 , 0
       0                 10083.9       0
Bank Sta=9883.546,10673.46
Exp/Cntr=0.3,0.1

Type RM Length L Ch R = 1 ,7709.272,434.593500,434.593500,434.593500
XS GIS Cut Line= 6
405334.731794834745874.347982407405446.095096469745876.344170958
405551.205440938745875.884628043405615.338066667745873.638441339
405753.629127383745863.281285062406055.977778912745856.457729876
#Sta/Elev= 30
9889.61879.816169909.89179.378499919.89378.451559929.896 75.69089939.89874.28357
9949.90171.151749959.90170.581979969.90269.356859979.903   69.269989.90467.59346
9999.905 64.572610019.9169.9254610029.9171.3362810039.9174.6220710049.9175.45744
10059.9175.4442810069.9173.6955510079.9168.9852910099.9176.0303810119.9176.63881
10139.9376.1849510149.9376.5774910179.97 76.233210210.0676.5567610270.2275.87619
 10560.478.29832 10570.479.31776 10580.483.17851 10590.4 86.277610611.3986.65323
#Mann= 3 , 0 , 0
9889.618  0.0643       09889.618  0.0643       010611.39  0.0643       0
#XS Ineff= 2 , 0
       0                10052.56       0
Bank Sta=9889.618,10611.39
Exp/Cntr=0.3,0.1

Type RM Length L Ch R = 1 ,7274.678,477.816600,477.816600,477.816600
XS GIS Cut Line= 6
 405319.18841207746400.574244738405391.942929417746377.167076513
405471.264737964746334.517959356405653.375198156746182.537899479
 405726.50449577746138.503524438406061.186112255745903.332729906
#Sta/Elev= 30
9736.76976.966149752.97376.600229763.54573.313079774.14171.70989 9827.7572.28328
9872.769 71.2003 9958.6470.36234 9971.7367.752159983.08368.548749998.59363.56367
   1000163.7039410012.7367.4955510027.5769.34226 10042.472.4319810052.7573.27742
10087.6570.4002710142.8172.6422110173.3775.1542810213.1175.8693310286.1576.00582
10335.4474.1714310387.8574.7696410422.78 76.295910510.1376.7556210518.0377.63209
10542.4276.78671 10591.276.65494 10603.481.4364210614.9584.9730910635.3386.16712
#Mann= 3 , 0 , 0
9736.769    0.04       09736.769    0.04       010635.33    0.04       0
#XS Ineff= 2 , 0
       0                10061.59       0
Bank Sta=9736.769,10635.33
Exp/Cntr=0.3,0.1

Type RM Length L Ch R = 1 ,6796.862,110.858400,110.858400,110.858400
XS GIS Cut Line= 3
 405316.13567096746528.026185155406030.267458916746805.209412798
406359.434125572746763.542746127
#Sta/Elev= 30
9607.14476.232389627.37975.856359648.83373.562069681.014  72.7099831.18970.77354
9852.643  69.6959970.639 69.50539981.36568.409389992.09264.0304710024.2765.98838
   1003567.6568210056.4566.92299 10068.668.0462510096.24 67.248810152.9967.91244
10163.7269.8944210270.9968.0058810303.1767.8510110324.6268.5506610335.3567.82826
 10372.668.2525410388.0369.0457810408.1967.7734710438.4367.6341410529.1569.54424
10579.5569.6115410589.6376.5601710599.7177.5375910650.1177.6420810704.9876.10013
#Mann= 3 , 0 , 0
9607.144  0.0418       09607.144  0.0418       010704.98  0.0418       0
#XS Ineff= 2 , 0
       0                10058.28       0
Bank Sta=9607.144,10704.98
Exp/Cntr=0.3,0.1

Type RM Length L Ch R = 2 , 6743.84,,,
Bridge Culvert--1,0,-1,-1, 0
Deck Dist Width WeirC Skew NumUp NumDn MinLoCord MaxHiCord MaxSubmerge Is_Ogee
31.929,47,2.6,0,53,53, , , 0.95, 0, 0,0,,
 9796.91 9801.67 9811.48 9812.38 9823.09 9833.79 9839.47 9844.50 9855.21 9865.91
 9867.46 9876.62 9887.33 9895.45 9898.03 9908.74 9919.45 9923.44 9930.15 9940.86
 9951.43 9951.57 9962.27 9972.98 9979.42 9983.69 9994.3910005.1010007.4110015.80
10026.5110035.4010037.2210047.9210058.6310063.3910069.3410080.0410090.7510091.38
10101.4610112.1610119.3710122.8710133.5810144.2810147.3610154.9910165.7010175.35
10176.4010187.1110193.87
   70.77   70.71   70.61   70.59   70.46   70.27   70.18   70.08   69.87   69.81
   69.80   69.68   69.46   69.41   69.38   69.18   69.20   69.19   69.05   68.88
   68.87   68.86   68.85   68.78   68.78   68.77   68.70   68.72   68.71   68.66
   68.63   68.62   68.61   68.65   68.64   68.68   68.71   68.69   68.73   68.73
   68.74   68.68   68.67   68.65   68.64   68.73   68.71   68.61   68.63   68.65
   68.64   68.46   68.44
                                                                                
                                                                                
                                                                                
                                                                                
                                                                                
                        
 9796.91 9801.67 9811.48 9812.38 9823.09 9833.79 9839.47 9844.50 9855.21 9865.91
 9867.46 9876.62 9887.33 9895.45 9898.03 9908.74 9919.45 9923.44 9930.15 9940.86
 9951.43 9951.57 9962.27 9972.98 9979.42 9983.69 9994.3910005.1010007.4110015.80
10026.5110035.4010037.2210047.9210058.6310063.3910069.3410080.0410090.7510091.38
10101.4610112.1610119.3710122.8710133.5810144.2810147.3610154.9910165.7010175.35
10176.4010187.1110193.87
   70.77   70.71   70.61   70.59   70.46   70.27   70.18   70.08   69.87   69.81
   69.80   69.68   69.46   69.41   69.38   69.18   69.20   69.19   69.05   68.88
   68.87   68.86   68.85   68.78   68.78   68.77   68.70   68.72   68.71   68.66
   68.63   68.62   68.61   68.65   68.64   68.68   68.71   68.69   68.73   68.73
   68.74   68.68   68.67   68.65   68.64   68.73   68.71   68.61   68.63   68.65
   68.64   68.46   68.44
                                                                                
                                                                                
                                                                                
                                                                                
                                                                                
                        
BR Coef=-1 , 0 , 0 ,, 0 ,,,0.8,-1,,0,
WSPro=,,,, 1 ,,,, 0 ,,,, 0 ,,,,-1 ,-1 ,-1 , 0 , 0 , 0 , 0 , 0
Culvert=2,3,8,47,0.013,0.4,1,8,1,64.33,10000,61.38,10000,Culvert #1, 0, 31.929
Culvert Bottom n=0.013
BC Design=,, 0 ,, 0 ,,,,,,

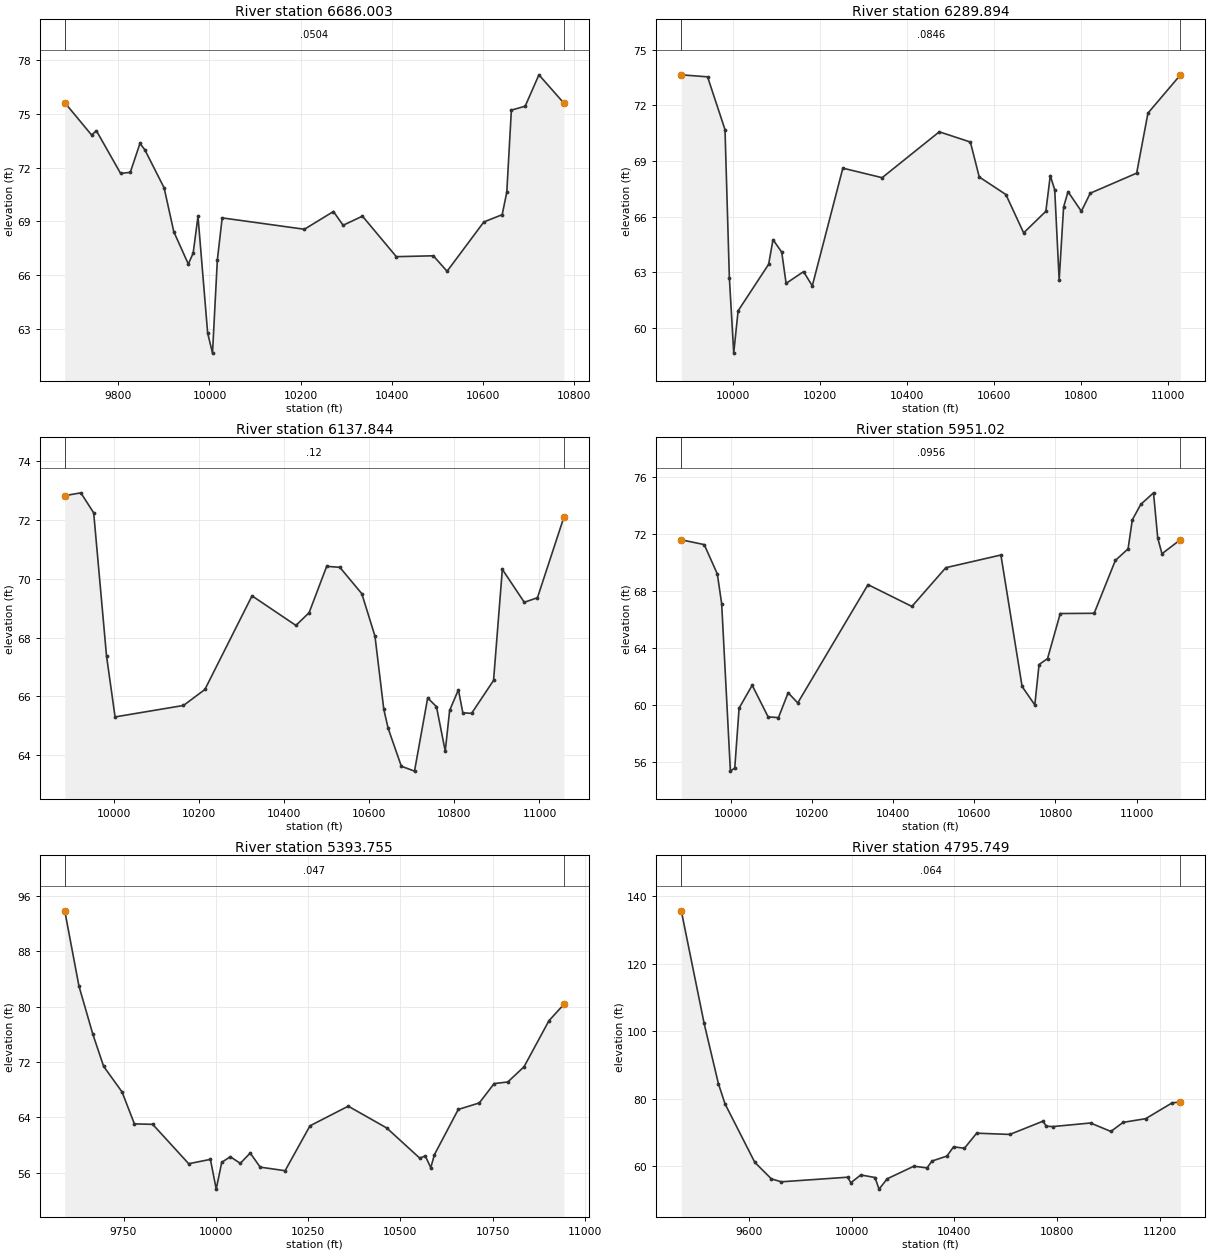
Type RM Length L Ch R = 1 ,6686.003,396.109900,396.109900,396.109900
XS GIS Cut Line= 3
405309.551152905746640.082590646406005.267458846746889.237190566
406359.434125503746843.403857238
#Sta/Elev= 30
9682.16475.634369741.06273.829469751.68474.065599804.79371.683889826.03771.74185
9847.28173.353239857.90373.008479900.39170.875719921.63568.42722  9953.566.62503
9964.12267.231489974.744 69.28339995.98862.7695510006.6161.6535510017.2366.85222
10027.8569.2015310208.4368.5672810272.1669.55711 10293.468.7895810335.8969.29947
10410.2467.0365310491.4667.0860210521.7166.2220610602.3868.9737410642.7169.38117
 10652.870.6366910662.8875.2159210693.1375.4336410723.3877.1857810778.27 75.6032
#Mann= 3 , 0 , 0
9682.164  0.0504       09682.164  0.0504       010778.27  0.0504       0
#XS Ineff= 2 , 0
       0                 10091.9       0
Bank Sta=9682.164,10778.27
Exp/Cntr=0.3,0.1

Type RM Length L Ch R = 1 ,6289.894,152.049900,152.049900,152.049900
XS GIS Cut Line= 3
 405244.85079217747009.376079455405780.267458856747059.376079485
406378.184125543746934.376079455
#Sta/Elev= 30
9880.51973.649729941.00473.541459981.104 70.69679991.148 62.723510001.1958.65029
10011.2360.9290810081.5463.4395210091.5864.7664410111.6764.0911810121.7162.41048
10161.8963.0432410181.9762.2750910252.2868.6197310342.6768.1062210474.1870.57851
10545.6970.0270710566.13 68.144510627.4267.1984110668.2965.1317810719.3766.29278
10729.5968.21846 10739.867.4510110750.0262.5854810760.2366.5272310770.4567.35186
 10801.166.2943410821.5367.2697710928.3268.3504710954.3471.5868611029.1173.64774
#Mann= 3 , 0 , 0
9880.519  0.0846       09880.519  0.0846       011029.11  0.0846       0
#XS Ineff= 2 , 0
       0                10228.98       0
Bank Sta=9880.519,11029.11
Exp/Cntr=0.3,0.1

Type RM Length L Ch R = 1 ,6137.844,186.823700,186.823700,186.823700
XS GIS Cut Line= 3
 405237.32299307747182.583331913405666.489659727747142.999998584
406385.239659727746961.749998584
#Sta/Elev= 30
9885.21472.814949923.05172.911059953.178 72.23149983.30667.3748810003.3965.30419
10164.0765.6933410214.2866.2350910324.9869.4141710428.1168.4101410459.05 68.8416
 10500.370.4157810531.2470.3825810582.81 69.487610613.7468.0446410634.3765.57014
10644.6864.9154810675.6263.6308410706.5663.46402 10737.565.9485810758.1365.65169
10778.7564.1443610789.0765.5258510809.6966.2261910820.0165.4443210840.63 65.4248
 10892.266.5438910912.8270.3128910964.3969.1953710995.3369.3511411057.4572.08789
#Mann= 3 , 0 , 0
9885.214    0.12       09885.214    0.12       011057.45    0.12       0
#XS Ineff= 2 , 0
       0                10220.82       0
Bank Sta=9885.214,11057.45
Exp/Cntr=0.3,0.1

Type RM Length L Ch R = 1 , 5951.02,557.264500,557.264500,557.264500
XS GIS Cut Line= 4
 405232.35079217 747403.12607947405444.850792199747319.792746112
405717.767458856747192.709412783 406388.60079217746990.626079455
#Sta/Elev= 30
9877.97471.578259934.527 71.24179966.75269.182669977.49367.093359998.97655.34148
10009.7255.5591310020.46  59.76710052.6861.3698310091.9759.1488610117.4359.09791
10141.2760.8432310164.9660.1298510338.0568.4309110446.1766.9017510529.72 69.6206
10665.49 70.510510717.7161.2822510749.0459.9879210759.4962.8253910780.37 63.2374
10811.7166.4026510895.2666.4194510947.4870.1305910978.8170.9426410989.2572.98087
11010.1474.0655311041.4774.8753411051.9171.7022211062.3670.6005911107.8971.59055
#Mann= 3 , 0 , 0
9877.974  0.0956       09877.974  0.0956       011107.89  0.0956       0
#XS Ineff= 2 , 0
       0                10228.28       0
Bank Sta=9877.974,11107.89
Exp/Cntr=0.3,0.1

Type RM Length L Ch R = 1 ,5393.755,598.006700,598.006700,598.006700
XS GIS Cut Line= 3
405344.265599936747978.372566119405597.737822145 747787.40034391
 406365.09893325747092.955899447
#Sta/Elev= 30
9590.73793.853199629.21882.98017 9666.7876.033249696.05171.386869745.90567.68601
9779.46563.069579828.996 63.00149926.57957.310729985.32857.9403110001.0953.64009
   1001657.5109210039.2858.3220510066.2557.3683210093.2258.85488 10120.256.81914
10187.6356.3001910255.0762.7881210358.7765.6277110463.0962.4736210552.5158.11505
10567.41 58.441510582.3256.7383710592.2458.6269910656.83 65.154910713.6266.09078
10754.0968.8927810790.9669.1235310835.01 71.324510902.4477.9735310943.0480.34426
#Mann= 3 , 0 , 0
9590.737   0.047       09590.737   0.047       010943.04   0.047       0
#XS Ineff= 2 , 0
       0                10229.77       0
Bank Sta=9590.737,10943.04
Exp/Cntr=0.3,0.1

Type RM Length L Ch R = 1 ,4795.749,403.014700,403.014700,403.014700
XS GIS Cut Line= 2
405828.748840094748276.950137287407056.071155488 746770.03923279
#Sta/Elev= 30
9337.022135.70059426.096102.27899481.40584.475739507.19978.465269623.273 61.0932
9687.75856.18996 9726.4555.319139984.39156.683469997.28855.0418610035.9857.35911
10091.1756.5902510107.0153.1466810138.68 56.207210242.3359.9374910293.92 59.4498
10312.8661.46426 10371.362.95882 10397.165.6906810439.5465.2791310487.0569.74315
10616.3569.3715310745.3273.3004510758.2271.8014610784.0171.7048410930.4372.76445
11009.61 70.255611057.11 72.948811145.1374.0453811248.3178.74379 11280.579.00327
#Mann= 3 , 0 , 0
9337.022   0.064       09337.022   0.064       0 11280.5   0.064       0
#XS Ineff= 2 , 0
       0                10172.59       0
Bank Sta=9337.022,11280.5
Exp/Cntr=0.3,0.1

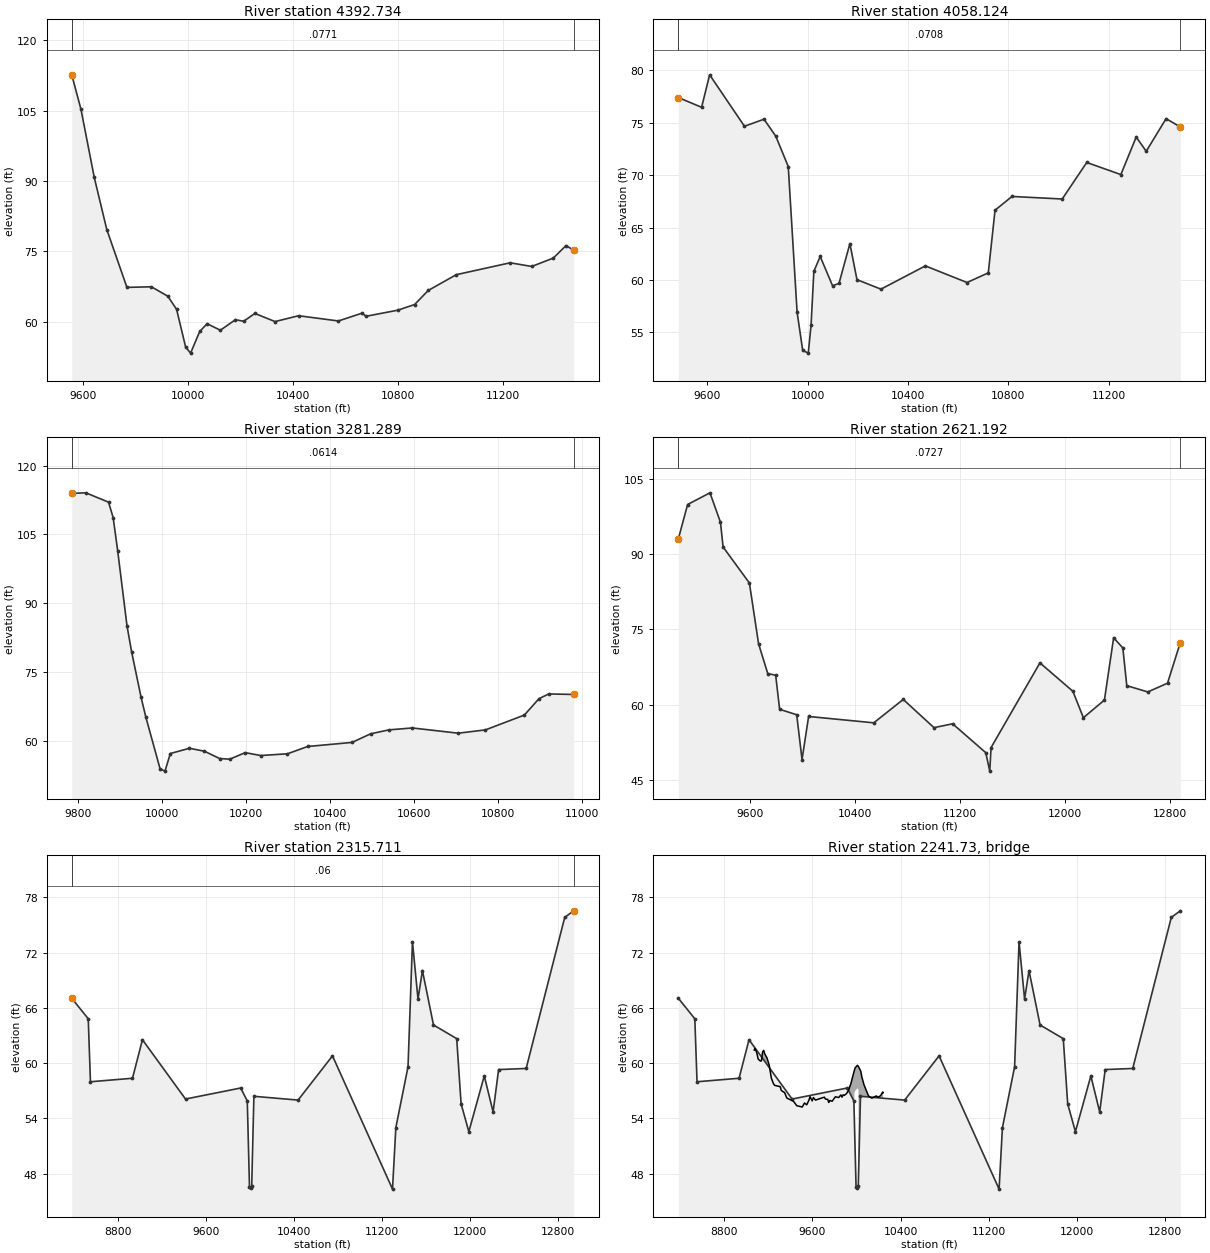
Type RM Length L Ch R = 1 ,4392.734,334.609500,334.609500,334.609500
XS GIS Cut Line= 6
405939.670305566748338.333165953406061.897800446748248.061654046
406290.031348884 748174.20220165406550.089242935748006.268092111
407086.609750658747545.411439493407451.904488802747204.935066134
#Sta/Elev= 30
9558.878 112.6659593.749105.34399644.40990.800239692.05979.677669768.77367.33455
9861.87367.459789924.45665.445769957.69662.648819992.22854.5871810010.9553.31457
10045.7257.9374210073.7759.5856210124.2758.19684 10181.460.43749 10212.960.11357
10255.5361.7810310332.16  60.04510421.9161.2893210573.21 60.1719 10663.461.84085
10678.4461.1721710798.7962.4669410863.2163.6758910915.2966.6891311021.7270.04373
11226.7772.5794111308.7971.7981811390.8173.5809711439.1776.24946 11468.675.27251
#Mann= 3 , 0 , 0
9558.878  0.0771       09558.878  0.0771       0 11468.6  0.0771       0
#XS Ineff= 2 , 0
       0                10272.25       0
Bank Sta=9558.878,11468.6
Exp/Cntr=0.3,0.1

Type RM Length L Ch R = 1 ,4058.124,776.835400,776.835400,776.835400
XS GIS Cut Line= 6
406187.117037266748714.091946274406416.898458123 748447.33975102
406649.235034645748293.545528635406979.714721441747904.089519769
407189.460662365747676.707185641407597.957879961747310.133891672
#Sta/Elev= 30
9484.22477.412749576.98176.483779609.03179.583669747.84774.672189825.73375.34365
9872.84873.720389922.48870.822039957.72656.92834 9980.0653.2621210002.3453.00451
10013.4155.6474110024.58 60.813410049.8862.2348110099.2459.4367110124.9259.66523
10168.3163.4647910196.4960.0210510292.1459.1133510469.2161.3356510635.4259.74803
10720.2160.6703910747.0566.6524810814.7767.9686811014.9667.72425 11112.771.21197
11248.8170.0588411310.0573.6429311349.9572.2831211429.1975.3992611485.9274.60281
#Mann= 3 , 0 , 0
9484.224  0.0708       09484.224  0.0708       011485.92  0.0708       0
#XS Ineff= 2 , 0
       0                 10142.2       0
Bank Sta=9484.224,11485.92
Exp/Cntr=0.3,0.1

Type RM Length L Ch R = 1 ,3281.289,660.096900,660.096900,660.096900
XS GIS Cut Line= 6
407164.863371044748756.200287297407221.127479345748624.088648498
407295.128430694748493.871324316407500.898738533748224.990372851
407741.575035632747987.797074035407936.499546617747873.501947224
#Sta/Elev= 30
9784.244113.96519817.682114.08659871.926112.05119882.921108.66859893.916101.2789
9915.90585.04851  9926.979.373819949.518 69.41769960.84165.103449994.81353.81347
10006.4253.3277510019.2157.1756310064.7558.31631 10100.557.67207 10136.756.07625
10160.8455.9352910197.7157.3681210234.36 56.730810298.4557.1139210346.5158.70519
10452.2759.5942510496.4561.47183 10540.2 62.335210595.95  62.75310705.5561.60903
10770.3362.3316210863.07 65.571210897.8569.1457410921.0370.1764410980.7370.06694
#Mann= 3 , 0 , 0
9784.244  0.0614       09784.244  0.0614       010980.73  0.0614       0
#XS Ineff= 2 , 0
       0                 10264.3       0
Bank Sta=9784.244,10980.73
Exp/Cntr=0.3,0.1

Type RM Length L Ch R = 1 ,2621.192,305.481700,305.481700,305.481700
XS GIS Cut Line= 6
406844.550104221748875.997051522407922.773828824748872.072322771
408822.748641719749032.194451675409313.489751269749097.886826187
410019.824666401749144.959795401 410642.29466783749145.159722775
#Sta/Elev= 30
9056.94193.042389127.391 99.90479297.393102.23389377.39496.362979397.39491.43245
9597.39684.253829667.396 72.12289737.39766.172399797.39865.864449827.39859.06224
9957.47357.96966  9997.949.0302410048.0457.6307910543.8956.3644810768.0461.02888
11001.8155.3988611143.6356.1705411395.9750.4097911426.1946.7297211436.2551.42835
11807.9968.3195912058.5162.6602712138.5857.3794812298.6860.9094412368.6973.32036
 12438.771.3073212468.7163.7760712628.7162.5253712778.7364.2647912876.0572.38282
#Mann= 3 , 0 , 0
9056.941  0.0727       09056.941  0.0727       012876.05  0.0727       0
#XS Ineff= 2 , 0
       09958.272        10127.68       0
Bank Sta=9056.941,12876.05
Exp/Cntr=0.3,0.1

Type RM Length L Ch R = 1 ,2315.711,149.810500,149.810500,149.810500
XS GIS Cut Line= 6
406226.187185794749270.914595619407091.125854641749197.277319252
407904.283019453749162.962140858409683.779626846749350.662932873
410262.174633235749372.291710898410766.658211827749365.043465629
#Sta/Elev= 30
8383.68867.035778533.20164.809198553.29457.97105 8934.8258.350469025.12462.53359
9415.99256.094239916.67957.292349976.68255.889859996.68346.4960710006.6946.44234
10016.6946.6048710036.6956.3917510437.6455.9813910749.9760.7820111294.6946.31373
11324.8752.9833811435.5159.6004511475.7473.1643511526.0466.9492911566.2470.03978
11666.6464.1351411877.2362.6526611917.2955.5643711987.4152.5545712127.56 58.6045
12207.6254.6902912257.6359.2936612507.6759.4148912857.7275.8176612939.4276.52867
#Mann= 3 , 0 , 0
8383.688    0.06       08383.688    0.06       012939.42    0.06       0
#XS Ineff= 2 , 0
       0 9901.08        10723.85       0
Bank Sta=8383.688,12939.42
Exp/Cntr=0.3,0.1

Type RM Length L Ch R = 3 , 2241.73,,,
BEGIN DESCRIPTION:
END DESCRIPTION:
Bridge Culvert--1,0,-1,-1, 0
Deck Dist Width WeirC Skew NumUp NumDn MinLoCord MaxHiCord MaxSubmerge Is_Ogee
53.415800,42.978900,2.6,0, 60, 60, , , 0.95, 0, 0,0,,
 9072.29 9077.57 9087.60 9097.62 9107.64 9127.69 9137.72 9147.74 9157.77 9167.79
 9187.84 9207.89 9227.94 9247.99 9258.01 9308.11 9318.13 9348.19 9368.23 9428.34
 9458.40 9508.10 9528.53 9548.57 9568.61 9578.63 9598.66 9608.68 9628.72 9708.87
 9718.89 9738.91 9748.92 9758.93 9778.95 9808.98 9839.01 9859.03 9869.04 9879.04
 9889.04 9909.04 9929.04 9949.05 9981.14 9981.14 9989.0510009.0510018.8610018.86
10039.0510049.0510069.0610109.1010139.1510179.2210199.2510219.2910239.3210242.33
   61.41   61.58   61.37   61.02   60.45   60.22   60.24   61.20   61.38   61.00
   60.57   59.80   58.35   57.73   57.58   57.44   57.02   56.79   56.20   55.86
   55.37   55.23   55.66   55.47   55.96   56.36   55.89   56.25   55.98   56.30
   56.09   56.06   55.72   55.94   55.85   56.34   56.26   56.54   56.30   56.55
   56.49   56.67   57.05   57.75   59.21   59.21   59.49   59.76   59.61   59.61
   59.13   58.48   57.63   56.44   56.19   56.43   56.29   56.47   56.86   56.78
 -938.59 -938.42 -938.63 -938.98 -939.55 -939.78 -939.76 -938.80 -938.62 -939.00
 -939.43 -940.20 -941.65 -942.27 -942.42 -942.56 -942.98 -943.21 -943.80 -944.14
 -944.63 -944.77 -944.34 -944.53 -944.04 -943.64 -944.11 -943.75 -944.02 -943.70
 -943.91 -943.94 -944.28 -944.06 -944.15 -943.66 -943.74 -943.46 -943.70 -943.45
 -943.51 -943.33 -942.95 -942.25 -940.79   56.71   56.99   57.26   57.11 -940.39
 -940.87 -941.52 -942.37 -943.56 -943.81 -943.57 -943.71 -943.53 -943.14 -943.22
 9072.29 9077.57 9087.60 9097.62 9107.64 9127.69 9137.72 9147.74 9157.77 9167.79
 9187.84 9207.89 9227.94 9247.99 9258.01 9308.11 9318.13 9348.19 9368.23 9428.34
 9458.40 9508.10 9528.53 9548.57 9568.61 9578.63 9598.66 9608.68 9628.72 9708.87
 9718.89 9738.91 9748.92 9758.93 9778.95 9808.98 9839.01 9859.03 9869.04 9879.04
 9889.04 9909.04 9929.04 9949.05 9981.14 9981.14 9989.0510009.0510018.8610018.86
10039.0510049.0510069.0610109.1010139.1510179.2210199.2510219.2910239.3210242.33
   61.41   61.58   61.37   61.02   60.45   60.22   60.24   61.20   61.38   61.00
   60.57   59.80   58.35   57.73   57.58   57.44   57.02   56.79   56.20   55.86
   55.37   55.23   55.66   55.47   55.96   56.36   55.89   56.25   55.98   56.30
   56.09   56.06   55.72   55.94   55.85   56.34   56.26   56.54   56.30   56.55
   56.49   56.67   57.05   57.75   59.21   59.21   59.49   59.76   59.61   59.61
   59.13   58.48   57.63   56.44   56.19   56.43   56.29   56.47   56.86   56.78
 -938.59 -938.42 -938.63 -938.98 -939.55 -939.78 -939.76 -938.80 -938.62 -939.00
 -939.43 -940.20 -941.65 -942.27 -942.42 -942.56 -942.98 -943.21 -943.80 -944.14
 -944.63 -944.77 -944.34 -944.53 -944.04 -943.64 -944.11 -943.75 -944.02 -943.70
 -943.91 -943.94 -944.28 -944.06 -944.15 -943.66 -943.74 -943.46 -943.70 -943.45
 -943.51 -943.33 -942.95 -942.25 -940.79   56.71   56.99   57.26   57.11 -940.39
 -940.87 -941.52 -942.37 -943.56 -943.81 -943.57 -943.71 -943.53 -943.14 -943.22
BR Coef=-1 , 0 , 0 ,, 0 ,,,0.8,0,1,0,
WSPro=,,,, 1 ,,,, 0 ,,,, 0 ,,,,-1 ,-1 ,-1 , 0 , 0 , 0 , 0 , 0
BC Design=,, 0 ,, 0 ,,,,,,