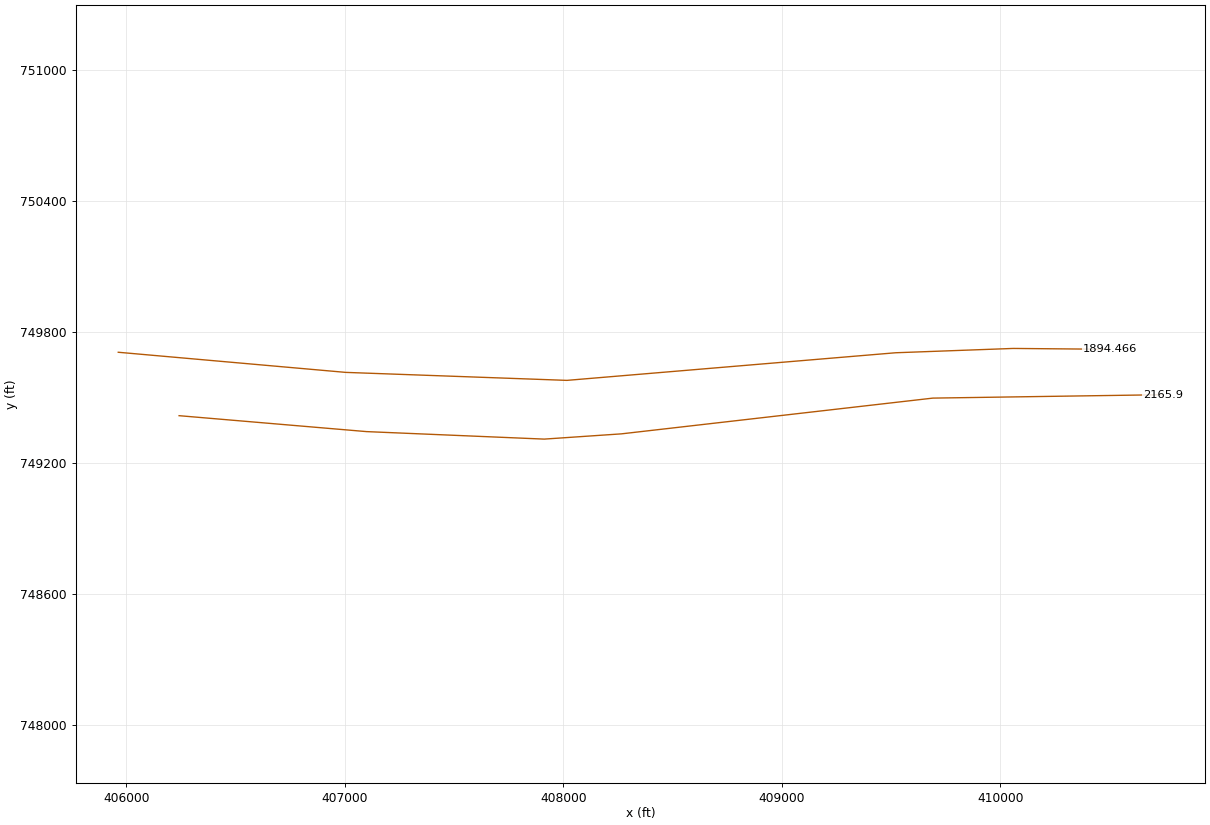
HEC-RAS study 2838_ras.prj: 2838

--- 2838_ras.g01 (geometry) --- (continued)

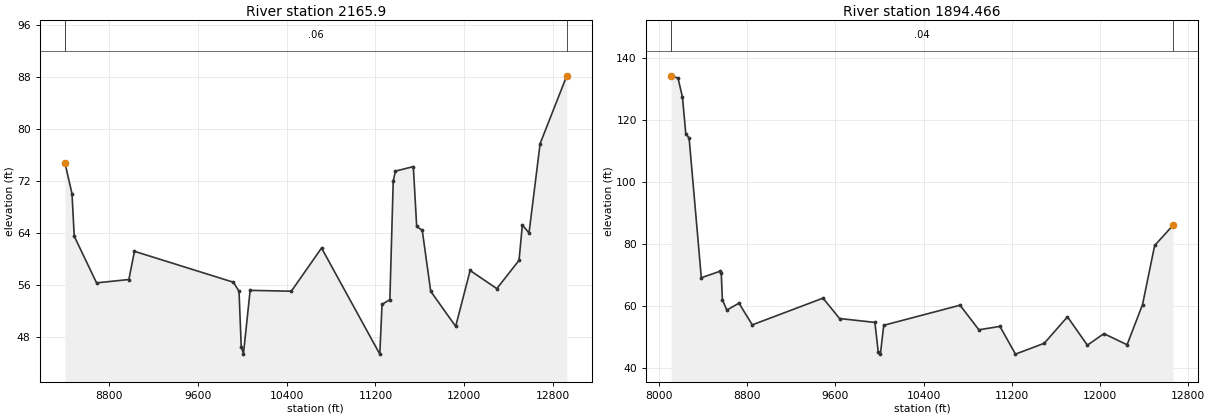
Type RM Length L Ch R = 1 ,  2165.9,271.433900,271.433900,271.433900
XS GIS Cut Line= 6
406241.256290764749417.412463158407099.459188044749344.499541461
407912.616352767749310.184363067408265.875852734749334.192403361
 409692.11296019749497.885155082410744.655590832749513.479373977
#Sta/Elev= 30
8403.91374.790238467.95770.036948488.049 63.50498688.975 56.33228980.04556.84903
9030.21361.178699921.79656.426989971.79955.03992  9991.846.48105 10011.845.45678
10071.8155.1821810442.7155.0524510714.6561.6872411239.2745.3865711259.4353.02533
11329.9453.7590311360.1171.9708711380.2373.4964311541.1674.1966611571.3264.99259
11621.5264.3972111697.7655.03403 11922.449.6500912052.6158.2344812292.7655.45061
12492.7959.7931412522.7965.2109712582.7964.0063412682.7977.7301912922.51 88.1368
#Mann= 3 , 0 , 0
8403.913    0.06       08403.913    0.06       012922.51    0.06       0
#XS Ineff= 2 , 0
       09611.681         10730.7       0
Bank Sta=8403.913,12922.51
Exp/Cntr=0.3,0.1

Type RM Length L Ch R = 1 ,1894.466,0.000000,0.000000,0.000000
XS GIS Cut Line= 6
  405962.7272034749707.764633556407004.068816728749615.624813875
408016.545282728749579.039939319409521.396029777749705.470657741
410059.638024992749725.260488962410501.230201433749721.334801387
#Sta/Elev= 30
8112.108134.25188174.729 133.5078214.929127.34698245.067115.56718275.205114.1973
8385.71169.174348556.49271.285458566.53870.635968576.58462.132668616.76858.75261
8727.24860.97602 8847.6653.992679489.01262.604629639.14756.03213 9959.3154.78076
9989.32545.3612310009.3344.6300510039.3353.8497410730.99 60.328610901.8652.40273
11092.83 53.503211233.4844.5606211494.4148.0549711704.9456.5889111885.1847.44916
12035.2851.1605612245.3247.5830712385.3260.5187312495.3379.5728512661.5986.09006
#Mann= 3 , 0 , 0
8112.108    0.04       08112.108    0.04       012661.59    0.04       0
#XS Ineff= 2 , 0
       09583.584        10719.89       0
Bank Sta=8112.108,12661.59
Exp/Cntr=0.3,0.1